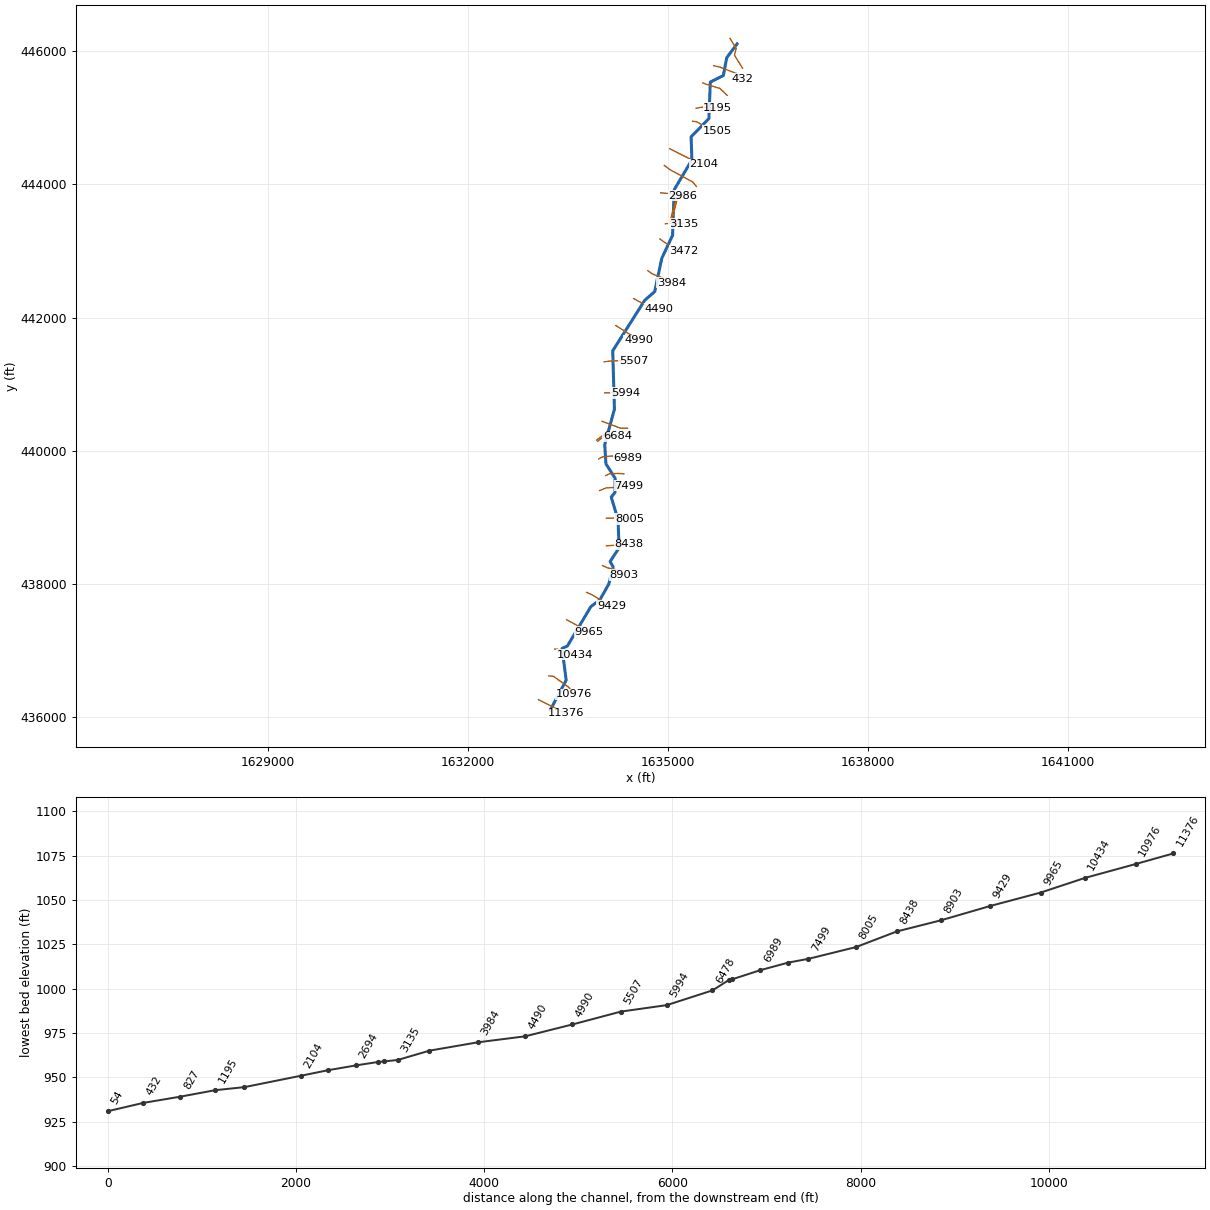
--- BLAKEFK.prj (project) ---

Proj Title=BLAKEFK
Current Plan=p01
Default Exp/Contr=0,0
English Units
Geom File=g01
Flow File=f01
Plan File=p01
BEGIN DESCRIPTION:
---------- MODELED AS PART OF WVEMD CTP PROGRAM, 2023----------
Stream Name: Blake Fork
Flood Zone:  AFH
Wetzel County, WV
HEC-RAS Version: RAS 6.3
Vertical Datum: NAVD88
Projection: NAD 1983 StatePlane West Virginia S FIPS 4702 (US Feet)
Terrain: 1-meter West Virginia FEMA R3 South Central (collected 2018-2020)
Land Use: 2019 NLCD
Hydrologic Method:
WV SIR2010-5033 regression equations
Additional Model Notes:
None
END DESCRIPTION:
DSS Export Rating Curves= 0
DSS Export Rating Curve Sorted= 0
DSS Export Volume Flow Curves= 0
DXF OffsetX= 0
DXF OffsetY= 0
DXF ScaleX= 0
DXF ScaleY= 0

--- BLAKEFK.p01 (plan) ---

Plan Title=Floodplain
Program Version=6.30
Short Identifier=Floodplain
Geom File=g01
Flow File=f01
Subcritical Flow
K Sum by GR= 0
Std Step Tol= 0.01
Critical Tol= 0.01
Num of Std Step Trials= 20
Max Error Tol= 0.3
Flow Tol Ratio= 0.001
Split Flow NTrial= 30
Split Flow Tol= 0.02
Split Flow Ratio= 0.02
Log Output Level= 0
Friction Slope Method= 1
Unsteady Friction Slope Method= 2
Unsteady Bridges Friction Slope Method= 1
Parabolic Critical Depth
Global Vel Dist= 0 , 0 , 0
Global Log Level= 0
CheckData=False
Encroach Param=-1 ,0,0, 0
Mapping Interval=1HOUR
Computation Time Step Use Courant=        0
Computation Time Step Use Time Series=    0
Computation Time Step Count To Double=0
Computation Time Step Max Doubling=0
Computation Time Step Max Halving=0
Computation Time Step Residence Courant=0
Run HTab= 0
Run UNet= 0
Run Sediment= 0
Run PostProcess= 0
Run WQNet= 0
Run RASMapper=-1
UNET Theta= 0
UNET Theta Warmup= 0
UNET ZTol= 0
UNET ZSATol= 0
UNET MxIter= 0
UNET Max Iter WO Improvement= 0
UNET MaxInSteps= 0
UNET DtIC= 0
UNET DtMin= 0
UNET MaxCRTS= 0
UNET WFStab= 0
UNET SFStab= 0
UNET WFX= 1
UNET SFX= 1
UNET Gravity=32.17405
UNET 1D Methodology=Finite Difference
UNET DSS MLevel= 1
UNET Pardiso=0
UNET DZMax Abort= 0
UNET Use Existing IB Tables= 0
UNET Froude Reduction=False
UNET Froude Limit= 0
UNET Froude Power= 0
UNET D1 Cores= 0
UNET WindReference=Eulerian
UNET WindDragFormulation=Hsu (1988)
UNET D2 Coriolis=0
UNET D2 Cores= 0
UNET D2 Theta= 1
UNET D2 Theta Warmup= 1
UNET D2 Z Tol= 0.01
UNET D2 Volume Tol= 0.01
UNET D2 Max Iterations= 20
UNET D2 Equation= 0
UNET D2 RampUpFraction=0.1
UNET D2 TimeSlices= 1
UNET D2 Turbulence Formulation=Non-Conservative (original)
UNET D2 Eddy Viscosity=0.3
UNET D2 Transverse Eddy Viscosity=0.1
UNET D2 Smagorinsky Mixing=0
UNET D2 BCVolumeCheck=0
UNET D2 Cores=0
UNET D2 SolverType=PARDISO (Direct)
UNET D2 Minimum Iterations= 3
UNET D2 Maximum Iterations= 30
UNET D2 Restart Number= 10
UNET D2 Relaxation Coeff=1.3
UNET D2 SOR Precondition Iterations= 10
UNET D2 ILUT Maximum Fill= 8
UNET D2 ILUT Tolerance=1E-08
UNET D2 Convergence Tolerance=0.00001
UNET D1D2 MaxIter= 0
UNET D1D2 ZTol=0.01
UNET D1D2 QTol=0.1
UNET D1D2 MinQTol=1
Write IC File= 0
Write IC File at Fixed DateTime=0
Write IC File at Sim End=0
Echo Input=False
Echo Parameters=False
Echo Output=False
Write Detailed= 0
HDF Write Warmup=0
HDF Write Time Slices=0
HDF Flush=0
HDF Compression= 1
HDF Chunk Size= 1
HDF Spatial Parts= 1
HDF Use Max Rows=0
HDF Fixed Rows= 1
Calibration Method= 0
Calibration Iterations= 20
Calibration Max Change=0.05
Calibration Tolerance=0.2
Calibration Maximum=1.5
Calibration Minimum=0.5
Calibration Optimization Method= 1
WQ AD Non Conservative
WQ ULTIMATE=-1
WQ Max Comp Step=1HOUR
WQ Output Interval=15MIN
WQ Output Selected Increments= 0
WQ Output face flow=0
WQ Output face velocity=0
WQ Output face area=0
WQ Output face dispersion=0
WQ Output cell volume=0
WQ Output cell surface area=0
WQ Output cell continuity=0
WQ Output cumulative cell continuity=0
WQ Output face conc=0
WQ Output face dconc_dx=0
WQ Output face courant=0
WQ Output face peclet=0
WQ Output face adv mass=0
WQ Output face disp mass=0
WQ Output cell mass=0
WQ Output cell source sink temp=0
WQ Output nsm pathways=0
WQ Output nsm derived pathways=0
WQ Create Restart=0
WQ Fixed Restart=0
WQ System Summary=0
WQ Write To DSS=0
Sorting and Armoring Iterations= 10
XS Update Threshold= 0.02
Bed Roughness Predictor= 0
Hydraulics Update Threshold= 0.02
Energy Slope Method= 1
Volume Change Method= 1
Sediment Retention Method= 0
Sediment TS Multiplier= 1
Warm Up Method= 0
XS Weighting Method= 0
Number of US Weighted Cross Sections= 1
Number of DS Weighted Cross Sections= 1
Upstream XS Weight=0
Main XS Weight=1
Downstream XS Weight=0
Number of DS XS's Weighted with US Boundary= 1
Upstream Boundary Weight= 1
Weight of XSs Associated with US Boundary= 0
Number of US XS's Weighted with DS Boundary= 1
Downstream Boundary Weight= 0.5
Weight of XSs Associated with DS Boundary= 0.5
Percentile Method= 0
Sediment Output Level= 3
Mass or Volume Output= 0
Output Increment Type= 1
Profile and TS Output Increment= 1
Transport Output Increment 1
XS Output Flag= 0
XS Output Increment= 10
Read HDF5 Sediment Hotstart= 0
Sediment Hotstart Type= 0
Write Gradation File= 0
Read Gradation Hotstart= 0
Write HDF5 File= 1
Write Binary Output= 1
Write DSS Sediment File= 0
DSS Sediment Output Type= 1
SV Curve= 0
Specific Gage Flag= 0
Subcell Erosion Methods= 0
Subcell Deposition Methods= 0
Advection Scheme= 1
Matrix Solver= 0
Implicit Weighting Factor= 1
Maximum Outer Loop Convergence Iterations= 5
Convergence Maximum Absolute= 0.001
Convergence RMSE= 0.0001
Grain Fractions Max Abs Error= 0.001
Max Subgrid Regions= 1
Max Subgrid Length Scale= 3.402823E+38
Initial Layer Thickness= 3.402823E+38
Min Layer Thickness= 3.402823E+38
Max Layer Thickness= 3.402823E+38
Number of Layers= 5

--- BLAKEFK.f01 (steady flow) ---

Flow Title=Flow
Program Version=4.00
Number of Profiles=1
Profile Names=F01pct
River Rch & RM=BLAKEFK,Main,11376
     538
River Rch & RM=BLAKEFK,Main,8438
     619
River Rch & RM=BLAKEFK,Main,6684
     689
River Rch & RM=BLAKEFK,Main,4990
    1400
Boundary for River Rch & Prof#=BLAKEFK,Main      ,1
Up Type=0
Dn Type=3
Dn Slope=0.011701

--- BLAKEFK.g01 (geometry) ---

Geom Title=Geometry
Program Version=6.31

River Reach=BLAKEFK         ,Main
Reach XY= 30
      1633235.82      436109.358 1633474.8342083436558.738303423
1633413.16284056437035.9224817911633493.00441749437071.861310637
1633844.34207847437661.147531149     1633981.133      437766.424
     1634115.767      438005.0011634179.77563871438259.509638707
     1634133.905      438339.962     1634268.926      438545.328
     1634252.663       438967.03     1634150.925      439307.417
     1634206.521      439375.117     1634209.169      439588.426
     1634071.501      439805.517     1634052.591      440093.712
     1634198.579      440626.228     1634172.861      441502.158
     1634652.429      442259.708     1634802.577      442390.947
     1634908.475      442889.803     1635070.348      443235.485
     1635094.553      443919.285     1635360.056      444367.839
     1635348.331        444713.9     1635615.346      444987.722
     1635636.526      445535.745     1635831.681      445633.701
     1635882.739      445901.094     1636037.434      446108.585

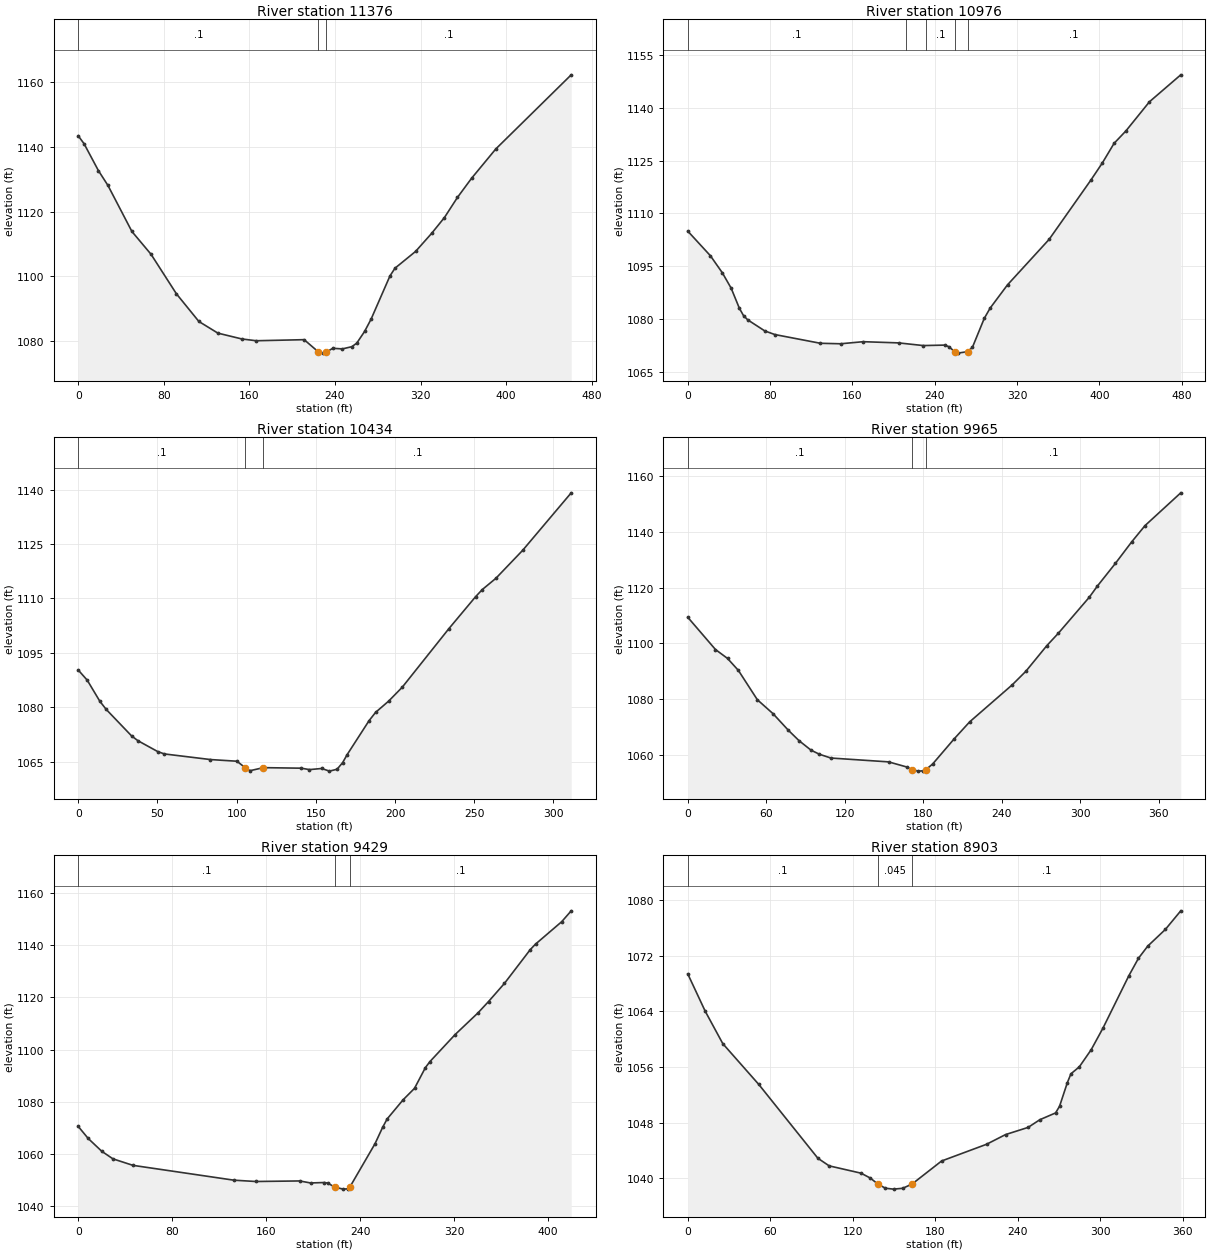
Type RM Length L Ch R = 1 ,11376   ,399.5,399.9,399
XS GIS Cut Line= 2
1633059.23855346436266.858239613 1633471.4206816436060.767175542
#Sta/Elev= 30
       0 1143.45     5.5 1140.98    18.9 1132.67    27.8 1128.09    50.2 1113.85
    68.1 1106.79    91.8 1094.58   112.8 1086.02   130.6 1082.41     153 1080.61
   166.4 1080.06   211.2 1080.39   224.6 1076.59     229 1076.23     232 1076.58
     238 1077.72   246.9 1077.54   255.8 1078.22   260.4 1079.33   267.7 1082.93
   273.8 1086.76   291.4 1100.09   296.1 1102.49   315.4 1107.69   330.3 1113.24
   342.3 1118.14   354.5 1124.38   367.7  1130.3   390.3 1139.35460.8336 1162.29
#Mann= 3 ,-1,0
       0      .1       0   224.6    .045       0     232      .1       0
Bank Sta=224.6,232
XS Rating Curve= 0 ,0
Exp/Cntr(USF)=0,0
Exp/Cntr=0.3,0.1

Type RM Length L Ch R = 1 ,10976   ,533.6,542.1,539.3
XS GIS Cut Line= 4
1633214.21373739436623.7520162021633285.81044368 436615.71756536
 1633513.0471117436453.4458900031633586.95181048 436349.01533738
#Sta/Elev= 30
       0 1104.95      22 1097.95    33.6 1093.11    42.2 1088.72    50.2    1083
    54.2 1080.93    58.3 1079.72    74.9 1076.57    84.7 1075.54   128.9 1073.06
   148.6 1072.92   170.6 1073.51     205 1073.17   228.9 1072.41   249.6 1072.54
   253.8  1072.1   259.5 1070.65   262.4 1070.26     2721070.677   276.7 1071.91
   288.2 1080.13   293.9 1083.05   310.8 1089.67   351.3 1102.61   391.6 1119.35
   402.9 1124.28   414.4  1129.9   425.9 1133.43   448.8 1141.72   479.2 1149.37
#Mann= 5 ,-1,0
       0      .1       0  212.05     .12       0  232.05      .1       0
   259.5    .045       0     272      .1       0
Bank Sta=259.5,272
XS Rating Curve= 0 ,0
Exp/Cntr(USF)=0,0
Exp/Cntr=0.3,0.1

Type RM Length L Ch R = 1 ,10434   ,468.3,469.2,466.4
XS GIS Cut Line= 4
1633302.42700102437025.2770703041633339.99533643437024.423244499
 1633491.9763297436980.0243026461633601.26603272436943.309793036
#Sta/Elev= 30
       0 1090.27     5.7 1087.46    13.7 1081.62    17.7 1079.39    33.7 1072.09
    37.7 1070.77    50.2 1067.77    54.4 1067.12    83.5 1065.57   100.2 1065.11
   105.41063.332   108.5  1062.5   116.9 1063.34   140.8 1063.19     146  1062.8
   153.7 1063.11   158.6 1062.38   163.4  1062.9   166.9 1064.71   169.8 1066.95
   183.6 1076.29   187.7 1078.57   195.9 1081.66   204.5 1085.49     234 1101.67
   250.9  1110.5   255.1 1112.45   263.6 1115.52   280.5 1123.23   311.2 1139.11
#Mann= 3 ,-1,0
       0      .1       0   105.4    .045       0   116.9      .1       0
Bank Sta=105.4,116.9
XS Rating Curve= 0 ,0
Exp/Cntr(USF)=0,0
Exp/Cntr=0.3,0.1

Type RM Length L Ch R = 1 ,9965    ,533.7,536,535.3
XS GIS Cut Line= 2
1633481.47715929437466.399087742 1633812.0239577437285.509304361
#Sta/Elev= 30
       0 1109.34    21.2 1097.76    30.4 1094.57    38.7 1090.27    53.2 1079.75
    65.2 1074.74      77 1068.75    85.1 1065.05    94.2 1061.67   100.6  1060.2
   109.4 1058.84   153.5 1057.46   167.2 1055.65   171.7 1054.58   176.3 1054.14
   180.1 1054.26   181.91054.636   187.2 1056.71   203.7 1065.76   215.5 1071.83
   247.9 1085.05   258.4 1089.95   274.4 1099.13   283.3 1103.63   306.9 1116.52
   313.1 1120.54   326.8 1128.63   339.3 1136.38   349.5 1142.22   376.8 1153.97
#Mann= 3 ,-1,0
       0      .1       0   171.7    .045       0   181.9      .1       0
Bank Sta=171.7,181.9
XS Rating Curve= 0 ,0
Exp/Cntr(USF)=0,0
Exp/Cntr=0.3,0.1

Type RM Length L Ch R = 1 ,9429    ,516.9,526.1,526.3
XS GIS Cut Line= 4
1633781.81125771437877.5448571111633863.79727463437839.805262017
1634044.68705802437731.7919381271634151.39901656437679.737324204
#Sta/Elev= 30
       0 1070.59     8.5 1065.97    20.1 1061.05    29.6 1058.16    46.6 1055.68
   132.6    1050   151.2  1049.5   188.5 1049.71   197.8 1048.94   209.6 1049.11
   212.5 1048.87   218.61047.301   225.7 1046.58     230 1046.73   231.21047.329
   252.7 1063.97   259.1 1070.16     263 1073.43   276.6 1080.76   286.3 1085.14
   295.6  1093.1   299.5 1095.41   320.9 1105.73   340.4 1114.04   349.3 1118.34
   362.8 1125.26   384.9 1138.25   389.3 1140.32   411.6  1148.9   419.7 1153.06
#Mann= 3 ,-1,0
       0      .1       0   218.6    .045       0   231.2      .1       0
Bank Sta=218.6,231.2
XS Rating Curve= 0 ,0
Exp/Cntr(USF)=0,0
Exp/Cntr=0.3,0.1

Type RM Length L Ch R = 1 ,8903    ,457.6,465.4,462.8
XS GIS Cut Line= 4
1634020.80680766438278.0127934781634098.10790933438244.047157893
1634239.82659574438213.5952087481634345.23718893438138.636564699
#Sta/Elev= 30
       0 1069.38    12.7 1064.02    25.5 1059.36    51.7  1053.5    94.7  1042.9
   102.9 1041.81   126.1 1040.76   132.9 1040.05   138.41039.189   143.8  1038.6
   149.7 1038.47   156.4 1038.59   163.2  1039.2   184.7 1042.51   217.4 1044.91
   231.2  1046.3   247.6 1047.33   256.2 1048.44   267.6 1049.41   270.5 1050.36
   276.2 1053.77   278.8 1055.03   284.9 1056.03   293.5 1058.48   302.1 1061.59
   320.9  1069.1   327.9 1071.61   334.7 1073.37   347.5 1075.76   358.7 1078.43
#Mann= 3 ,-1,0
       0      .1       0   138.4    .045       0   163.2      .1       0
Bank Sta=138.4,163.2
XS Rating Curve= 0 ,0
Exp/Cntr(USF)=0,0
Exp/Cntr=0.3,0.1

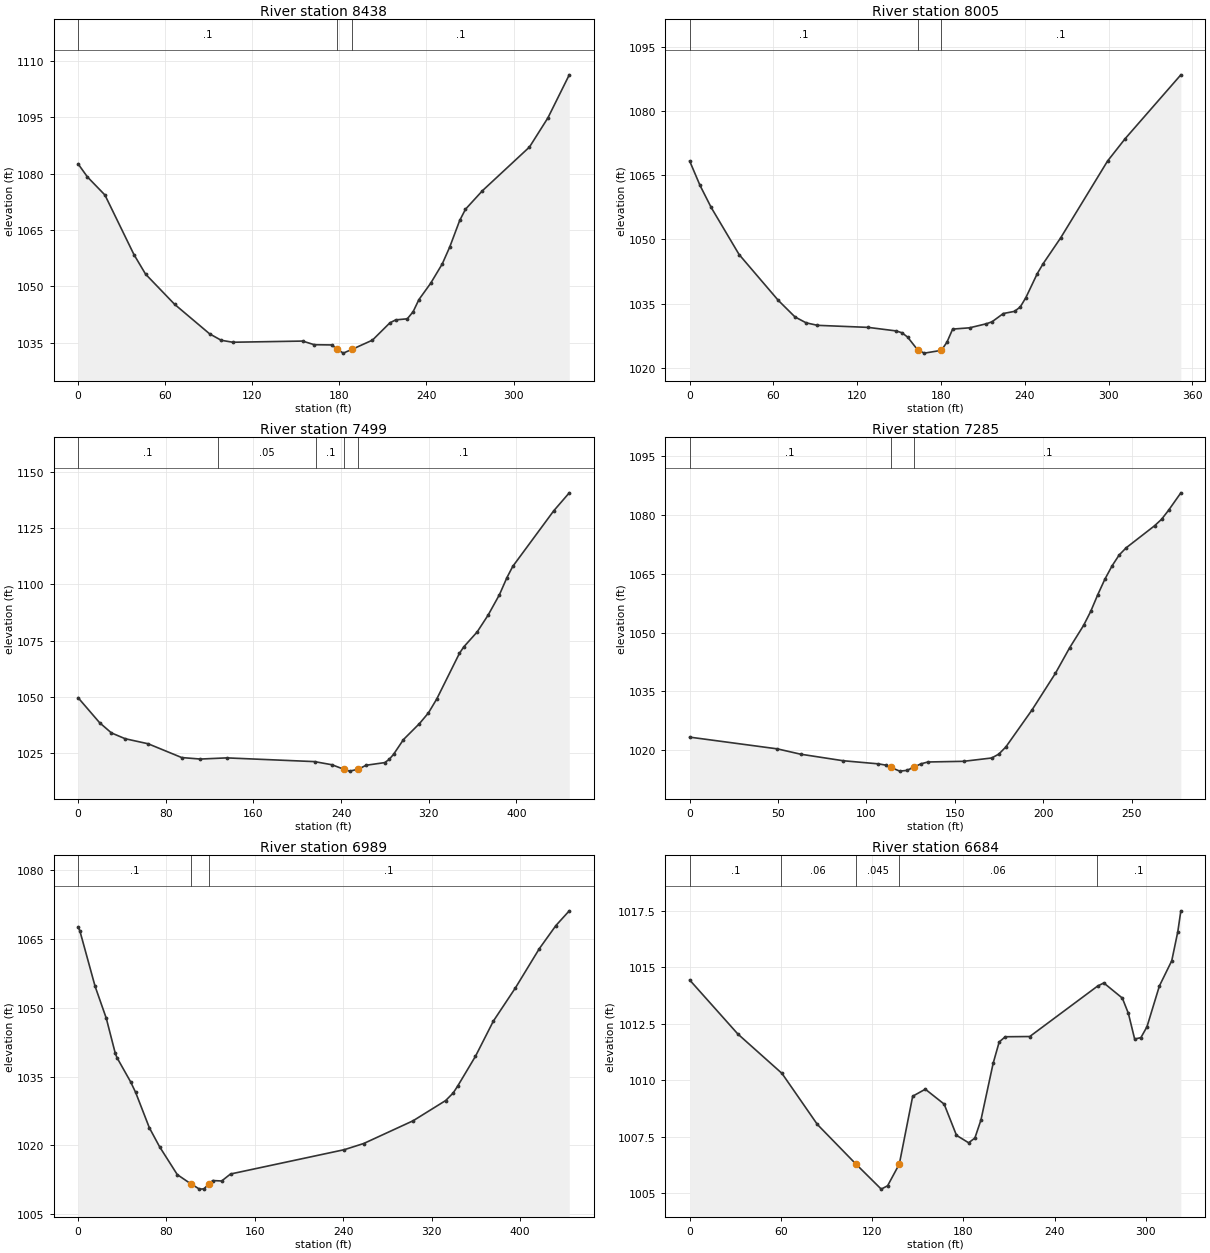
Type RM Length L Ch R = 1 ,8438    ,431.4,433,432.4
XS GIS Cut Line= 4
1634077.69435782438576.0448487151634142.20564086 438579.83963007
 1634331.9447086438591.2239741351634415.42989841438596.916146168
#Sta/Elev= 30
       0 1082.64     6.4 1079.17    18.5 1074.34    38.5 1058.47    46.5 1053.27
    66.5 1045.24    90.6 1037.38    98.6 1035.66   106.6 1035.14   154.7 1035.45
   162.7 1034.48   174.7 1034.42   178.7 1033.26   182.7 1032.24     1891033.293
   202.8  1035.7   214.8  1040.3   218.8 1041.09   226.8 1041.38   230.8 1043.25
   234.8 1046.49   242.9 1050.84   250.9    1056   256.1 1060.55   262.9 1067.56
   266.9 1070.56   278.6  1075.5     311 1087.13   323.7  1094.9   338.4 1106.35
#Mann= 3 ,-1,0
       0      .1       0   178.7    .045       0     189      .1       0
Bank Sta=178.7,189
XS Rating Curve= 0 ,0
Exp/Cntr(USF)=0,0
Exp/Cntr=0.3,0.1

Type RM Length L Ch R = 1 ,8005    ,504.3,505.4,501.9
XS GIS Cut Line= 4
1634076.72111871 438989.571592511634159.87836445 438989.57159251
1634321.50794068439010.6537111491634422.23361863438979.030533191
#Sta/Elev= 30
       0 1068.27     7.4 1062.59    15.4 1057.44    35.4 1046.45    63.4 1035.77
    75.4 1031.89    83.4 1030.51    91.5 1029.93   127.8 1029.45   147.9 1028.62
     152 1028.19     156  1027.2   163.5 1024.09   168.1 1023.44   180.2 1024.09
   184.2 1025.99   188.3 1029.05   200.4 1029.35   212.5  1030.3   216.5 1030.76
   224.6 1032.69   232.6 1033.19   236.7 1034.22   240.7 1036.39   248.9 1042.01
   253.1 1044.33   265.7 1050.38   299.2 1068.28   311.8  1073.5   351.7 1088.41
#Mann= 3 ,-1,0
       0      .1       0   163.5    .045       0   180.2      .1       0
Bank Sta=163.5,180.2
XS Rating Curve= 0 ,0
Exp/Cntr(USF)=0,0
Exp/Cntr=0.3,0.1

Type RM Length L Ch R = 1 ,7499    ,214,214,213.6
XS GIS Cut Line= 4
 1633976.2775388439405.1628334981634075.88821977 439445.32843066
1634316.88180274439458.1814217521634414.88585982439475.854284504
#Sta/Elev= 30
       0 1049.52    19.7 1038.35    30.4 1033.84      43 1031.24    63.9    1029
    94.6 1022.85   111.6 1022.19   135.7 1022.71   215.8 1021.05   231.8 1019.64
   242.91017.576   247.8 1016.81   255.8 1017.66   262.8 1019.42   279.9 1020.61
   283.9 1022.04   287.9 1024.27     297 1030.89   311.6 1038.01   319.8 1042.78
   327.4    1049     348 1069.24     352 1072.16   364.2  1078.8   374.2 1086.29
   384.6 1095.45   391.4 1103.02   396.7 1108.01   434.1 1132.78   448.3  1140.8
#Mann= 5 ,-1,0
       0      .1       0   127.4     .05       0   217.4      .1       0
   242.9    .045       0   255.8      .1       0
Bank Sta=242.9,255.8
XS Rating Curve= 0 ,0
Exp/Cntr(USF)=0,0
Exp/Cntr=0.3,0.1

Type RM Length L Ch R = 1 ,7285    ,296,296.3,295.3
XS GIS Cut Line= 4
1634068.03236625439629.2817564941634121.45207105439656.865026716
1634253.68388681439661.8347832531634339.02799083439656.823012425
#Sta/Elev= 30
       0 1023.35    49.6 1020.36    62.8    1019    86.8 1017.34   106.8 1016.54
   110.8 1016.23   113.71015.672   118.8 1014.69   122.8 1014.87   126.8 1015.68
   130.8 1016.54   134.8 1017.02     155 1017.19   170.9 1018.04   174.9 1019.03
   178.9 1020.86   193.7 1030.29   206.9 1039.59   214.9 1046.06   222.9 1051.84
   226.9 1055.39   230.9 1059.65   234.9 1063.58     239    1067     243 1069.76
     247  1071.6     263 1077.19     267 1078.86     271 1081.18   277.9 1085.59
#Mann= 3 ,-1,0
       0      .1       0   113.7    .045       0   126.8      .1       0
Bank Sta=113.7,126.8
XS Rating Curve= 0 ,0
Exp/Cntr(USF)=0,0
Exp/Cntr=0.3,0.1

Type RM Length L Ch R = 1 ,6989    ,299.1,305,306.2
XS GIS Cut Line= 4
1633962.71570481 439879.240552591634018.93468785439910.863730548
1634160.65337425439923.7472474941634396.07036572439889.781611909
#Sta/Elev= 30
       0 1067.69     1.6 1066.81    15.4  1054.7    25.5 1047.75    33.7 1040.05
    35.3  1039.1    47.5 1033.88    52.1 1031.55    64.5 1023.84    73.7 1019.72
    89.8 1013.61   101.8 1011.64   109.9 1010.44   113.9  1010.5   118.7 1011.64
   121.9 1012.31     130 1012.22     138 1013.74     241 1019.05   258.6  1020.4
   303.3 1025.36   332.8 1029.78   339.6 1031.43   343.7 1032.95   359.8 1039.45
     376 1047.13     396 1054.39   417.5  1062.9   432.6 1067.98   444.7 1071.19
#Mann= 3 ,-1,0
       0      .1       0   101.8    .045       0   118.7      .1       0
Bank Sta=101.8,118.7
XS Rating Curve= 0 ,0
Exp/Cntr(USF)=0,0
Exp/Cntr=0.3,0.1

Type RM Length L Ch R = 1 ,6684    ,37,28.2,27.3
XS GIS Cut Line= 5
1633946.34885884440145.1298199731634036.60133291440214.963182263
1634090.50778801440229.2565605091634148.49806546440234.565529572
1634242.01759742440218.230240148
#Sta/Elev= 30
       0 1014.44    31.7 1012.05    60.7 1010.31      84 1008.05   109.2 1006.31
     126 1005.19   130.2 1005.34   137.9  1006.3   146.7  1009.3     155 1009.61
   167.4 1008.95   175.5 1007.57   183.5 1007.24   187.6 1007.45   191.6 1008.25
   199.6 1010.75   203.6  1011.7   207.6 1011.93   223.7 1011.94   268.3 1014.17
   272.4 1014.31   284.6 1013.64   288.6 1012.96   292.7 1011.83   296.8 1011.89
   300.8 1012.37     309 1014.18   317.1 1015.29   321.1 1016.58   323.1  1017.5
#Mann= 5 ,-1,0
       0      .1       0      60     .06       0   109.2    .045       0
   137.9     .06       0  268.12      .1       0
Bank Sta=109.2,137.9
XS Rating Curve= 0 ,0
Exp/Cntr(USF)=0,0
Exp/Cntr=0.3,0.1

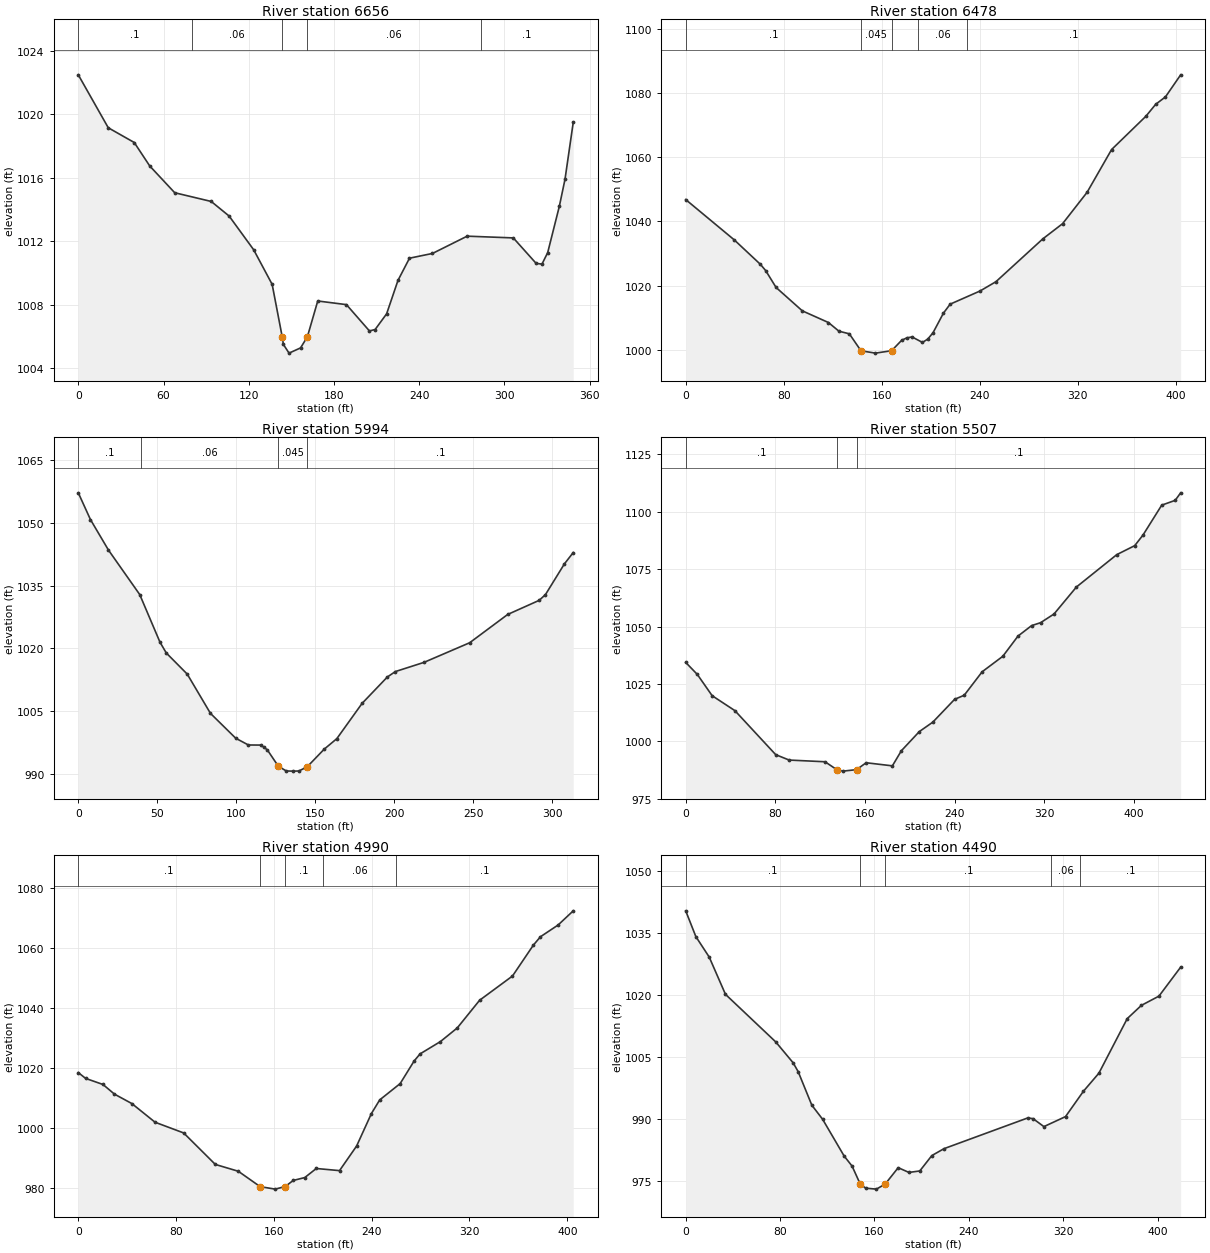
Type RM Length L Ch R = 1 ,6656    ,181.3,177.5,175.4
XS GIS Cut Line= 4
1633931.23871612440162.2818738691634040.27677303440244.366703227
1634146.45615429440259.068463709 1634249.7768599440241.508027577
#Sta/Elev= 30
       0  1022.5    21.1 1019.16    39.4 1018.23    50.3 1016.75    67.9 1015.06
    93.6 1014.51   106.2 1013.59   123.5 1011.46   136.5 1009.28   143.6 1005.96
   144.4 1005.49   148.4 1004.94   156.5 1005.27   161.3 1005.97   168.6 1008.23
   188.8    1008     205 1006.34     209 1006.43   217.1 1007.42   225.1 1009.53
   233.2 1010.93   249.4 1011.23   273.8 1012.32   306.3 1012.21   322.4  1010.6
   326.5 1010.56   330.5 1011.28   338.7  1014.2   342.7 1015.91   348.5  1019.5
#Mann= 5 ,-1,0
       0      .1       0      80     .06       0   143.6    .045       0
   161.3     .06       0  283.67      .1       0
Bank Sta=143.6,161.3
XS Rating Curve= 0 ,0
Exp/Cntr(USF)=0,0
Exp/Cntr=0.3,0.1

Type RM Length L Ch R = 1 ,6478    ,480.8,484.1,489
XS GIS Cut Line= 3
1634010.90368315440445.0093549891634287.24299163440342.185426253
1634396.49341592440342.185426253
#Sta/Elev= 30
       0 1046.79    39.7 1034.22      61 1026.62    65.3 1024.68    73.8 1019.42
    95.2 1012.15   116.5 1008.52   125.1 1005.82   133.6    1005   143.1999.7205
   154.9  998.99   168.1999.7425   176.3 1002.98   180.5 1003.74   184.8 1004.03
   193.3 1002.32   197.6 1003.36   201.9 1005.32   210.4 1011.43   215.9 1014.23
   240.3 1018.33   253.3 1021.23   291.5 1034.54   307.7 1039.29   327.7 1049.05
   347.7 1062.36   375.7 1072.72   383.7 1076.44   391.7 1078.76   404.1 1085.62
#Mann= 5 ,-1,0
       0      .1       0   143.1    .045       0   168.1      .1       0
     190     .06       0     230      .1       0
Bank Sta=143.1,168.1
XS Rating Curve= 0 ,0
Exp/Cntr(USF)=0,0
Exp/Cntr=0.3,0.1

Type RM Length L Ch R = 1 ,5994    ,486.2,487.5,487.6
XS GIS Cut Line= 2
1634052.38090767440872.1720179911634365.77173985440868.205045432
#Sta/Elev= 30
       0 1057.14     7.7 1050.76    19.1 1043.48    38.9 1032.86    51.7 1021.51
    55.7 1018.92      69 1013.86    83.7 1004.49    99.7  998.56   107.7  996.95
   115.7  996.93   117.6   996.4   119.7  995.78   126.7991.8575   131.7  990.75
   135.7  990.71   139.7  990.74     145991.7605   155.7  995.95   163.7  998.46
   179.7 1006.88   195.7 1013.18   200.8 1014.48   218.9 1016.67   247.8 1021.35
   271.9 1028.11   291.8 1031.47   295.8 1032.84   307.8 1040.18   313.4 1042.89
#Mann= 4 ,-1,0
       0      .1       0      40     .06       0   126.7    .045       0
     145      .1       0
Bank Sta=126.7,145
XS Rating Curve= 0 ,0
Exp/Cntr(USF)=0,0
Exp/Cntr=0.3,0.1

Type RM Length L Ch R = 1 ,5507    ,521.8,516.9,511.2
XS GIS Cut Line= 4
1634044.84230241441335.7380289991634109.10725787441346.984396204
1634327.60810644 441358.230763411634485.05724731441351.804267864
#Sta/Elev= 30
       0 1034.42    10.4 1029.15    23.6 1019.91    43.9  1013.4    80.3  994.23
    92.3  991.88   124.3  991.14   134.9 987.667   140.3  987.06   152.4   987.7
     161  990.71   184.4  989.36   192.4  995.93   208.4 1004.27   220.5 1008.41
   239.9 1018.33   248.5 1020.12   264.5 1030.34   282.9 1037.07   296.5  1045.9
   308.6 1050.44   316.6 1051.71   328.6  1055.5   348.6 1067.26   384.6 1081.36
   400.6 1085.27     408  1089.9   424.7 1102.91   436.7    1105   441.6 1108.28
#Mann= 3 ,-1,0
       0      .1       0   134.9    .045       0   152.4      .1       0
Bank Sta=134.9,152.4
XS Rating Curve= 0 ,0
Exp/Cntr(USF)=0,0
Exp/Cntr=0.3,0.1

Type RM Length L Ch R = 1 ,4990    ,498.7,499.6,499.7
XS GIS Cut Line= 3
1634219.00983364441881.918618222 1634462.6254268441729.658872498
1634558.66618949441661.727601329
#Sta/Elev= 30
       0 1018.54       6  1016.6    20.2 1014.58    29.6 1011.37    43.8 1008.24
    62.8 1002.03    86.2  998.47   112.1     988   130.9  985.73   148.8980.6104
   161.1  979.79   169.3  980.66   175.8  982.67   185.3  983.64   194.7  986.65
   213.7  985.94   227.7  994.13   239.8 1004.93   246.6 1009.46   263.3 1014.87
   274.7 1022.37   279.6 1024.75   296.2 1028.83     310 1033.37   328.3 1042.58
   355.2 1050.64   372.3 1060.92   378.1  1063.7   392.5 1067.59   404.9 1072.31
#Mann= 5 ,-1,0
       0      .1       0   148.8    .045       0   169.3      .1       0
     200     .06       0     260      .1       0
Bank Sta=148.8,169.3
XS Rating Curve= 0 ,0
Exp/Cntr(USF)=0,0
Exp/Cntr=0.3,0.1

Type RM Length L Ch R = 1 ,4490    ,500.2,506.8,506.9
XS GIS Cut Line= 3
1634486.67587233442286.7864095111634770.37351821442129.321202395
1634865.37318861442131.923933091
#Sta/Elev= 30
       0 1040.48     8.6 1034.24    19.9  1029.3    33.7 1020.27    76.3 1008.76
      91 1003.72    95.3 1001.57   106.9  993.44     116  990.05   134.3  981.13
     141  978.71     148   974.3   152.6  973.36   161.6  973.13     169974.3297
   180.1  978.32   189.2  977.17   198.4  977.53   208.6  981.25   218.9  982.92
   289.9  990.36   294.4  990.18   303.6  988.26   321.9  990.68   337.1  996.82
   350.2 1001.19   374.2 1014.39   386.2  1017.6   401.1 1019.84   419.5 1026.85
#Mann= 5 ,-1,0
       0      .1       0     148    .045       0     169      .1       0
     310     .06       0  334.47      .1       0
Bank Sta=148,169
XS Rating Curve= 0 ,0
Exp/Cntr(USF)=0,0
Exp/Cntr=0.3,0.1

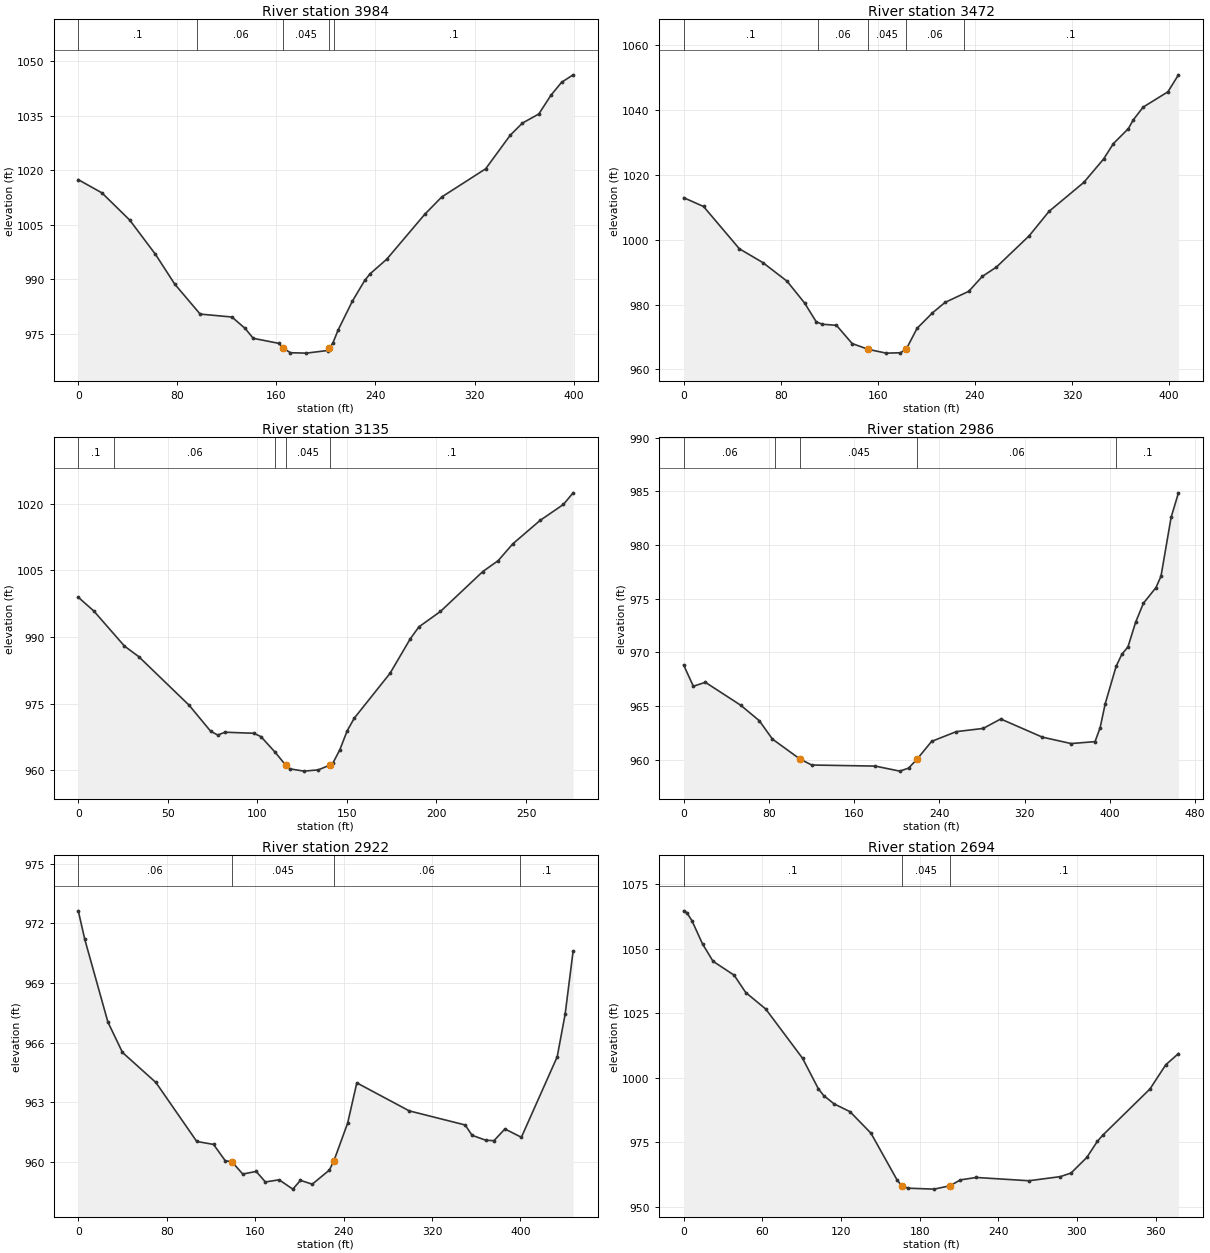
Type RM Length L Ch R = 1 ,3984    ,510.5,511.2,506.5
XS GIS Cut Line= 4
1634697.89661967442704.9618945641634768.74873307442655.799203637
1634933.58834382442592.1768977321635052.15718665442524.216707333
#Sta/Elev= 30
       0 1017.38    19.1 1013.75    41.6 1006.25    62.3  996.88    77.9  988.68
    98.4  980.45   124.1  979.64   134.7  976.52   141.3  973.79     162   972.4
   165.6  971.08   171.3  969.83   184.2  969.72   201.3  970.44   202.7  971.06
   205.6   972.5   209.9  976.12   221.3  983.97   231.3  989.68   235.6   991.5
   249.1  995.53   279.7 1007.82   293.5 1012.62     329 1020.37   348.8 1029.58
   358.7 1032.93   371.9 1035.42   381.7 1040.57   390.3 1044.13   399.6 1046.18
#Mann= 5 ,-1,0
       0      .1       0   96.24     .06       0   165.6    .045       0
   202.7     .06       0  206.24      .1       0
Bank Sta=165.6,202.7
XS Rating Curve= 0 ,0
Exp/Cntr(USF)=0,0
Exp/Cntr=0.3,0.1

Type RM Length L Ch R = 1 ,3472    ,330.8,337.6,347.2
XS GIS Cut Line= 4
1634878.78975294443182.1014156411634960.77576987443123.539974977
1635121.23411729 443031.012898731635240.69945624443007.588322465
#Sta/Elev= 30
       0 1012.93    16.4 1010.22    45.9  997.19    65.2  992.95    85.2   987.2
    99.6  980.51   109.2  974.71   114.2  973.94   125.9  973.61   138.8     968
   152.3  966.18   166.9  965.04   178.5  965.15   183.3  966.18   192.3  972.67
     205  977.44   215.4  980.67   234.9  984.08     246  988.65   257.7  991.55
   284.7 1001.19   301.1 1008.73   329.7 1017.63     346 1024.84   354.1  1029.6
   366.4  1034.2   370.4 1036.86   378.6 1040.83     399 1045.55   407.7 1050.78
#Mann= 5 ,-1,0
       0      .1       0  110.75     .06       0   152.3    .045       0
   183.3     .06       0  230.75      .1       0
Bank Sta=152.3,183.3
XS Rating Curve= 0 ,0
Exp/Cntr(USF)=0,0
Exp/Cntr=0.3,0.1

Type RM Length L Ch R = 1 ,3135    ,112.9,148.7,218.4
XS GIS Cut Line= 3
1634962.36372606443409.0777182531635172.14872632443422.909696292
1635237.46640039443412.919934375
#Sta/Elev= 30
       0  998.92     8.7  995.81    25.8  987.92    33.8  985.54    61.9  974.61
    73.9  968.76    77.9   967.9    81.9  968.54      98   968.3     102  967.55
     110     964   115.8961.1305     118   960.3     126  959.78     134  960.06
   140.3  961.11   142.1  961.53   146.1  964.64   150.1  968.81   154.1   971.7
   174.1  981.81   185.4  989.58   190.2  992.25   202.2  995.71   225.9 1004.71
   234.5 1007.17   242.6 1010.93   257.9 1016.22   270.9 1019.81   276.3 1022.42
#Mann= 5 ,-1,0
       0      .1       0      20     .06       0     110      .1       0
   115.8    .045       0   140.3      .1       0
Bank Sta=115.8,140.3
XS Rating Curve= 0 ,0
Exp/Cntr(USF)=0,0
Exp/Cntr=0.3,0.1

Type RM Length L Ch R = 1 ,2986    ,54.1,64.4,37.7
XS GIS Cut Line= 4
1635029.64601399443435.8518668191635062.33299142443468.444510157
1635139.17731385443778.8955728081635221.91229152443832.288007015
#Sta/Elev= 30
       0  968.82     9.1  966.84    20.4  967.21    53.6  965.07      71  963.63
    83.3  961.92   109.1960.0609   120.2   959.5   179.8   959.4   202.8  958.93
   211.1  959.21   219.1  960.05   232.7   961.7   255.8  962.61   281.1  962.91
   297.6  963.79   336.6   962.1   363.6   961.5   386.1  961.68   390.9  962.99
   395.7  965.23   405.9   968.7   411.2  969.81     417  970.51   424.2  972.81
   431.5  974.58   443.3  976.04     448   977.1   457.5  982.59   464.4  984.87
#Mann= 5 ,-1,0
       0     .06       0   86.16      .1       0   109.1    .045       0
   219.1     .06       0  405.98      .1       0
Bank Sta=109.1,219.1
XS Rating Curve= 0 ,0
Exp/Cntr(USF)=0,0
Exp/Cntr=0.3,0.1

Type RM Length L Ch R = 1 ,2922    ,276.7,227.7,183.5
XS GIS Cut Line= 5
1635019.88257397443455.8313906541635044.65879725443488.424033991
1635093.12740076 443672.566291331635123.04000614443787.348448276
 1635201.9103983443845.066311073
#Sta/Elev= 30
       0  972.63     5.9  971.19    26.8  967.03      40   965.5    70.2  963.99
   107.2  961.02   122.4  960.87   133.1  960.04   138.8  960.01   148.8  959.38
     161  959.51   169.3  958.98   181.7  959.09   194.1  958.62     201  959.06
   211.7  958.87   227.2  959.58   231.3  960.05   243.7  961.94     252  963.97
   299.4  962.56     350  961.85   356.3  961.33   368.8  961.08   376.1  961.06
     386  961.65   400.9  961.23   433.3  965.28   440.5  967.43   447.7   970.6
#Mann= 4 ,-1,0
       0     .06       0   138.8    .045       0   231.3     .06       0
  399.97      .1       0
Bank Sta=138.8,231.3
XS Rating Curve= 0 ,0
Exp/Cntr(USF)=0,0
Exp/Cntr=0.3,0.1

Type RM Length L Ch R = 1 ,2694    ,309.3,301.2,294.6
XS GIS Cut Line= 2
1634893.76041468443873.6842446091635269.72486373443839.718609024
#Sta/Elev= 30
       0 1064.68     2.4 1064.01     6.4 1060.78    14.4 1051.85    22.4 1045.13
    38.5 1039.73    47.4 1032.98    62.6 1026.62    90.7 1007.51   102.8  995.64
   106.8  993.06   114.8   989.8   126.9   986.8   142.9  978.44     163  960.15
   166.4 958.087     171  957.12   191.1  956.75   203.2  958.06   211.2  960.34
   223.3  961.27   263.4     960   287.5  961.61   295.6  963.02   307.6  969.06
   315.6  975.27   319.7  977.65   355.8  995.62   367.8 1004.98   377.5 1009.32
#Mann= 3 ,-1,0
       0      .1       0   166.4    .045       0   203.2      .1       0
Bank Sta=166.4,203.2
XS Rating Curve= 0 ,0
Exp/Cntr(USF)=0,0
Exp/Cntr=0.3,0.1

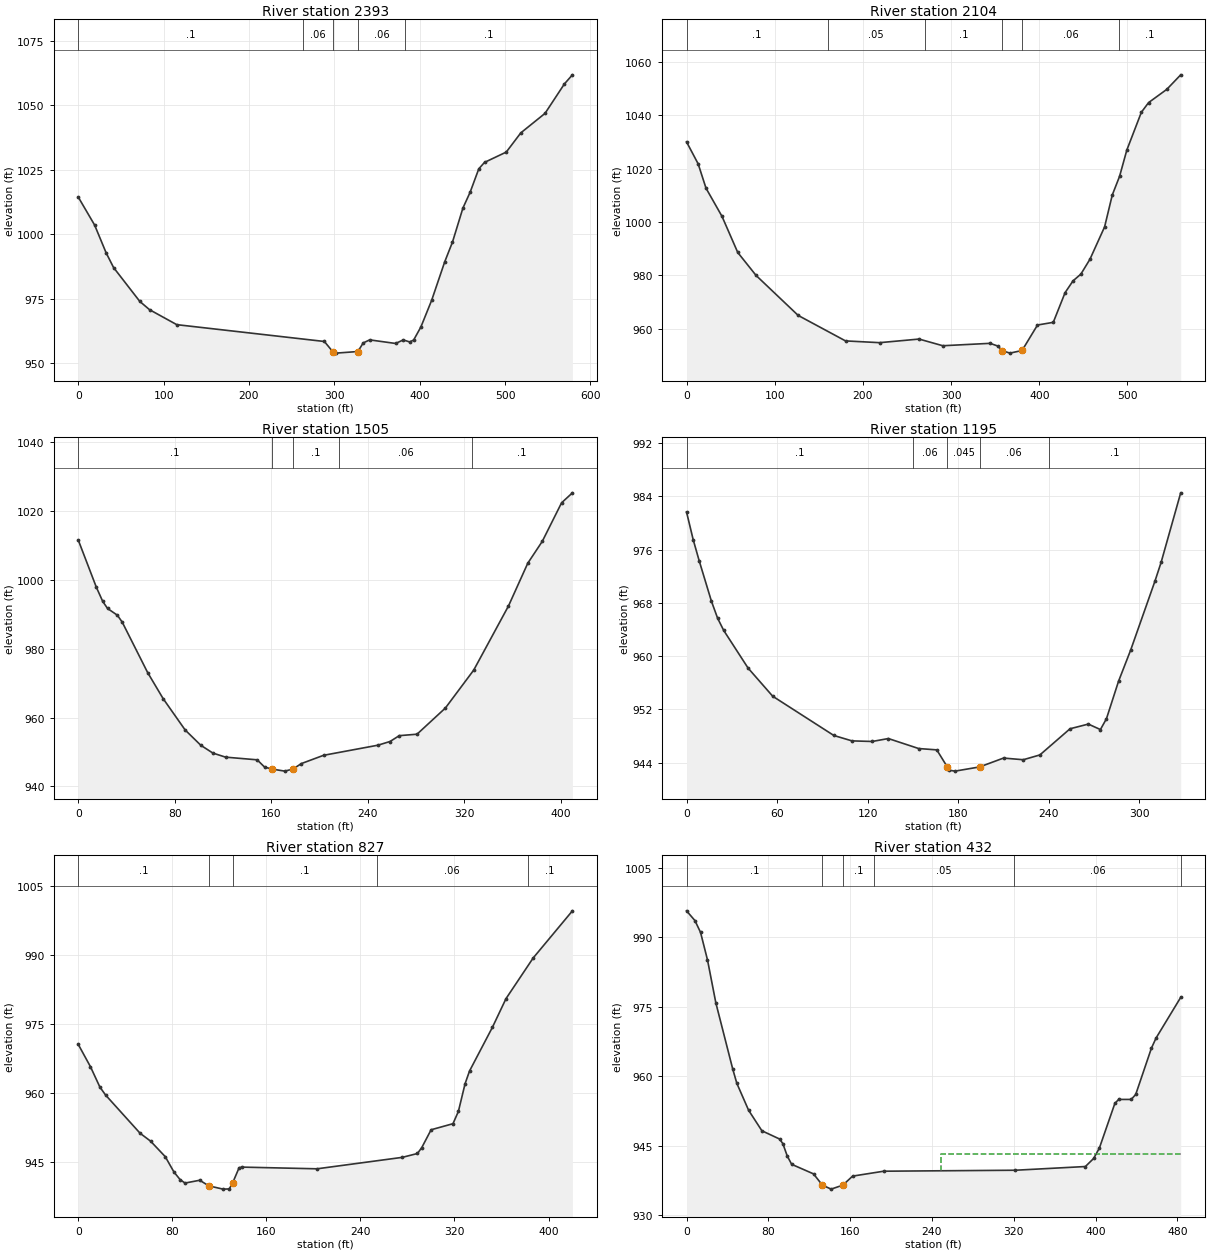
Type RM Length L Ch R = 1 ,2393    ,288.3,289.1,288.9
XS GIS Cut Line= 4
1634946.68710321444283.8415065121635037.78267757444217.327277611
1635371.79978357444036.5820903791635426.74632049443970.067861478
#Sta/Elev= 30
       0  1014.4    19.2 1003.55    32.7  992.78    41.4  987.11    72.1  974.01
    83.5  970.81   115.4  965.01   288.3   958.5   298.1  954.58   301.9  953.99
   327.6  954.61   333.8  957.94   341.4  959.12   371.8  957.73   380.7   959.1
   388.3  958.32   392.9  959.06   401.4  964.13     414  974.44   429.3  989.34
   438.4  996.98   450.6 1010.13   459.1  1016.3   469.2 1025.33   475.9 1027.82
   501.4 1031.82   518.4 1039.24   546.8  1046.8   569.5  1058.2   578.9 1061.72
#Mann= 5 ,-1,0
       0      .1       0  262.79     .06       0   298.1    .045       0
   327.6     .06       0  382.79      .1       0
Bank Sta=298.1,327.6
XS Rating Curve= 0 ,0
Exp/Cntr(USF)=0,0
Exp/Cntr=0.3,0.1

Type RM Length L Ch R = 1 ,2104    ,597.2,598.7,597.2
XS GIS Cut Line= 3
1635028.31949367 444534.702892591635458.16046814 444319.19679095
1635535.46156981444300.457129937
#Sta/Elev= 30
       0 1030.03    13.2 1021.77    22.1 1012.66    40.2 1002.12    58.1  988.57
    78.9  979.96   126.6  964.99   180.3  955.44     219  954.78   263.7  956.13
   290.6  953.63   344.3  954.53   353.3  953.47   357.7  951.83   366.7  950.86
   380.5  951.85     398  961.39   415.9   962.4   429.3  973.53   438.3  977.94
   447.2  980.47   457.5  986.05   474.1  998.17   482.8 1010.11   491.1 1017.13
   499.3 1026.95   515.8 1041.12     524 1044.74   544.6 1049.69   560.4 1055.14
#Mann= 6 ,-1,0
       0      .1       0     160     .05       0     270      .1       0
   357.7    .045       0   380.5     .06       0  490.84      .1       0
Bank Sta=357.7,380.5
XS Rating Curve= 0 ,0
Exp/Cntr(USF)=0,0
Exp/Cntr=0.3,0.1

Type RM Length L Ch R = 1 ,1505    ,305.4,309.6,313.2
XS GIS Cut Line= 4
1635371.87953227444947.2005115971635427.82910914444942.039943405
1635673.32680182444804.0842409251635745.15360037444803.232730265
#Sta/Elev= 30
       0 1011.56      15  997.85    20.3  993.73    24.3  991.68    32.4  989.73
    36.4  987.75    57.5  973.09    70.3  965.54    88.6  956.41   101.6  951.96
   111.6   949.7   122.1  948.52   148.3  947.74   154.4  945.65   160.3  945.07
   171.2  944.46   177.9  945.06     185  946.66   203.3  949.05   248.4  951.99
   258.4  953.06   266.1  954.76   280.8  955.18   304.3  962.78   327.8   973.8
   356.6  992.41   372.6 1004.83   384.6 1011.16   400.6 1022.36   409.6 1025.26
#Mann= 5 ,-1,0
       0      .1       0   160.3    .045       0   177.9      .1       0
  216.19     .06       0  326.19      .1       0
Bank Sta=160.3,177.9
XS Rating Curve= 0 ,0
Exp/Cntr(USF)=0,0
Exp/Cntr=0.3,0.1

Type RM Length L Ch R = 1 ,1195    ,366.9,367.9,364.7
XS GIS Cut Line= 4
1635423.78825883445143.8288473941635522.41434953445159.743070386
 1635700.8773865445145.041309904 1635749.0085231445150.258503771
#Sta/Elev= 30
       0  981.65     4.4   977.5     8.4  974.31    16.5  968.25    20.6   965.7
    24.6  963.88    40.8  958.21    57.1  953.99    97.6   948.1   109.6  947.29
     123   947.2   133.7  947.64   153.8  946.14   165.8  945.94  172.74  943.39
   173.9  942.89   177.9  942.75   194.2943.3825     210  944.71   223.1  944.46
   234.1  945.18   254.1  949.11   266.2  949.81   274.2  948.99   278.2  950.61
   286.2  956.23   294.3  960.95   310.4  971.31   314.4  974.07   327.4  984.52
#Mann= 5 ,-1,0
       0      .1       0   149.9     .06       0  172.74    .045       0
   194.2     .06       0   239.9      .1       0
Bank Sta=172.74,194.2
XS Rating Curve= 0 ,0
Exp/Cntr(USF)=0,0
Exp/Cntr=0.3,0.1

Type RM Length L Ch R = 1 ,827     ,391.6,395.1,393.4
XS GIS Cut Line= 4
1635522.31227931445522.3398955281635572.79284979445503.701573738
1635781.74834682445439.7117908171635888.69280405445337.486134769
#Sta/Elev= 30
       0   970.6    10.4  965.74    18.4  961.32    23.2   959.6    52.6  951.27
    61.5  949.56      74  946.18    81.4  942.84    86.6   941.2    90.8  940.44
   103.3  941.05     111939.8372   123.1  939.12   128.4  939.16   131.2940.4119
   136.8  943.77   139.1  943.91   203.1  943.54   275.6  946.03   288.5  946.87
   292.2  948.17   300.1  952.03   318.7  953.35   323.3  956.01     329  962.05
   332.8  964.82   352.2  974.29   363.8  980.55   386.9  989.39   420.3  999.65
#Mann= 5 ,-1,0
       0      .1       0     111    .045       0   131.2      .1       0
  253.81     .06       0  382.35      .1       0
Bank Sta=111,131.2
XS Rating Curve= 0 ,0
Exp/Cntr(USF)=0,0
Exp/Cntr=0.3,0.1

Type RM Length L Ch R = 1 ,432     ,384.9,378.6,352
XS GIS Cut Line= 5
1635688.06439971445780.7735223351635779.42024714445760.862632509
 1635925.8238488445704.6436494731636041.27599745445659.104966657
1636116.80779457445580.902045199
#Sta/Elev= 30
       0  995.69     8.2  993.59    13.7  991.04    20.5  985.09    28.7  975.78
    45.1  961.59    49.2  958.43    60.7  952.62    73.7  948.19      91  946.41
    94.2  945.41    98.5  942.73   102.8  940.95   124.2  938.88   132.8  936.46
   141.4  935.59  152.81  936.45   162.4   938.4   192.8  939.46   321.6  939.67
     390  940.47   398.1  942.22   403.7  944.47   418.8  954.09   422.5  954.96
   434.8  954.96   439.2  956.03   454.6  966.05   459.1  968.22   483.2     977
#Mann= 6 ,-1,0
       0      .1       0   132.8    .045       0  152.81      .1       0
   183.5     .05       0  320.33     .06       0  483.16      .1       0
#XS Ineff= 2 , 0
                          248.74          943.25
Permanent Ineff=
       F       F
Bank Sta=132.8,152.81
XS Rating Curve= 0 ,0
Exp/Cntr(USF)=0,0
Exp/Cntr=0.3,0.1

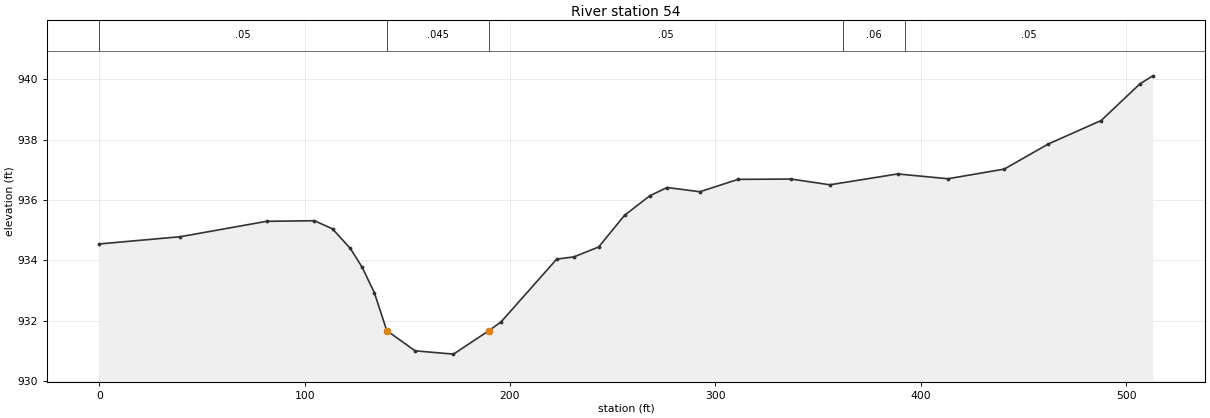
Type RM Length L Ch R = 1 ,54      ,,,
XS GIS Cut Line= 4
1635931.60232172 446192.04278839 1636024.3065521446039.247275462
1635998.70343622445938.9187864931636120.96997587445743.202214369
#Sta/Elev= 30
       0  934.54    39.5  934.78    81.5  935.29   104.8  935.31   113.6  935.04
   122.3  934.39   128.1  933.76     134  932.92  140.02  931.67   153.8     931
   172.5  930.89   189.8  931.67   195.7  931.96   222.8  934.04   231.1  934.11
   243.2  934.44   255.8  935.49   268.2  936.14   276.5  936.41   292.5  936.27
   311.1  936.68     337  936.69   355.8   936.5   388.8  936.86   413.3   936.7
   440.7  937.02   462.1  937.85   487.9  938.63   506.7  939.84     513  940.11
#Mann= 5 ,-1,0
       0     .05       0  140.02    .045       0   189.8     .05       0
  362.26     .06       0  392.26     .05       0
Bank Sta=140.02,189.8
XS Rating Curve= 0 ,0
Exp/Cntr(USF)=0,0
Exp/Cntr=0.3,0.1
LCMann Table=0

Chan Stop Cuts=-1
Use User Specified Reach Order=0
Composite Channel Slope=5